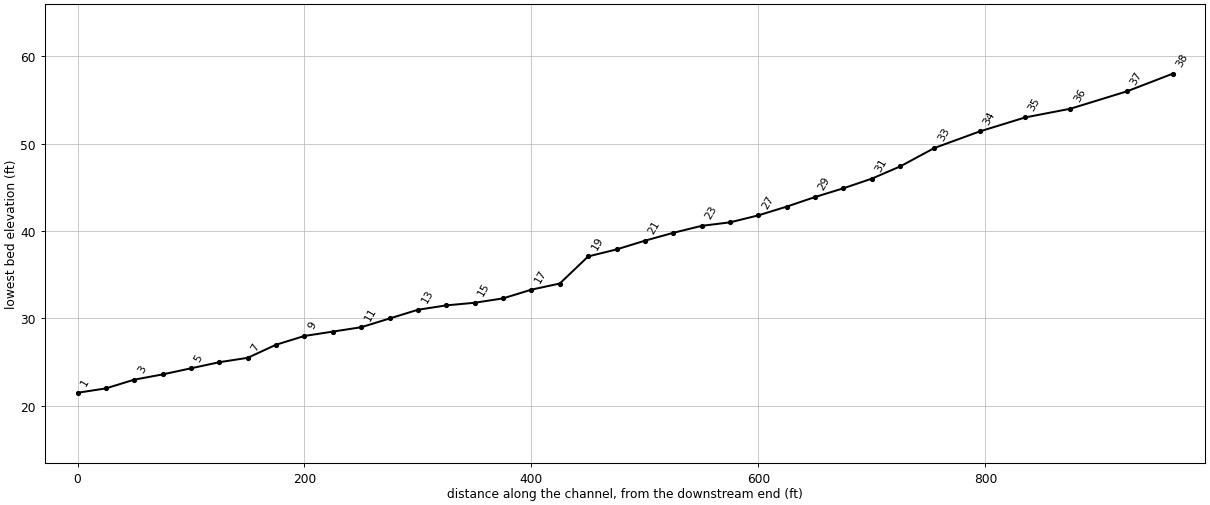
--- North.prj (project) ---

Proj Title=Glendale Camino North Channel
Current Plan=p01
Default Exp/Contr=0.3,0.1
English Units
Geom File=g01
Flow File=f06
Flow File=f01
Flow File=f02
Flow File=f03
Flow File=f04
Flow File=f05
Plan File=p01
Y Axis Title=Elevation
X Axis Title(PF)=Main Channel Distance
X Axis Title(XS)=Station
BEGIN DESCRIPTION:
END DESCRIPTION:
DSS Export Rating Curves= 0
DSS Export Rating Curve Sorted= 0
DSS Export Volume Flow Curves= 0
DXF OffsetX= 0
DXF OffsetY= 0
DXF ScaleX= 1
DXF ScaleY= 10

--- North.p01 (plan) ---

Plan Title=Plan 01
Program Version=3.11
Short Identifier=Plan 01
Geom File=g01
Flow File=f06
Mixed Flow
K Sum by GR= 0
Std Step Tol= 0.01
Critical Tol= 0.01
Num of Std Step Trials= 20
Max Error Tol= 0.3
Flow Tol Ratio= 0.001
Split Flow NTrial= 30
Split Flow Tol= 0.02
Split Flow Ratio= 0.02
Log Output Level= 0
Friction Slope Method= 1
Unsteady Friction Slope Method= 2
Unsteady Bridges Friction Slope Method= 1
Parabolic Critical Depth
Global Vel Dist= 0 , 0 , 0
Global Log Level= 0
CheckData=True
Encroach Param=-1 ,0,0, 0
Computation Interval=1HOUR
Output Interval=1HOUR
Run HTab= 0
Run UNet= 0
Run PostProcess= 0
UNET Theta= 1
UNET Theta Warmup= 1
UNET ZTol= 0.02
UNET ZSATol= 0.05
UNET MxIter= 20
UNET MaxInSteps= 0
UNET DtIC= 0
UNET DtMin= 0
UNET MaxCRTS= 20
UNET WFStab= 2
UNET SFStab= 1
UNET WFX= 1
UNET SFX= 1
UNET DSS MLevel= 4
UNET DZMax Abort= 100
UNET Convert EG Bridges=-1
UNET Use Existing IB Tables=-1
UNET Froude Reduction=False
UNET Froude Limit= 1
UNET Froude Power= 10
Instantaneous Interval=1HOUR
Write IC File= 0
Echo Input=False
Echo Output=False
Write Detailed= 0
Detailed Automatic Start=False, 10

--- North.f06 (steady flow) ---

Flow Title=Flow 06
Program Version=3.11
Number of Profiles= 1
Profile Names=PF 1
River Rch & RM=El Camino,Glendale        ,38
    3100
River Rch & RM=El Camino,Glendale        ,32
    3100
River Rch & RM=El Camino,Glendale        ,21
     581
River Rch & RM=El Camino,Glendale        ,19
     470
River Rch & RM=El Camino,Glendale        ,17
     470
River Rch & RM=El Camino,Glendale        ,16
     470
River Rch & RM=El Camino,Glendale        ,15
     470
River Rch & RM=El Camino,Glendale        ,14
     470
River Rch & RM=El Camino,Glendale        ,12
     370
River Rch & RM=El Camino,Glendale        ,9
     320
River Rch & RM=El Camino,Glendale        ,8
     250
River Rch & RM=El Camino,Glendale        ,7
     120
Boundary for River Rch & Prof#=El Camino,Glendale        , 1
Up Type= 3
Up Slope=0.03
Dn Type= 3
Dn Slope=0.03
DSS Import GetInterval= 0
DSS Import GetPeak= 0
DSS Import FillOption= 0

--- North.f01 (steady flow) ---

Flow Title=Flow 01
Program Version=3.11
Number of Profiles= 1
Profile Names=PF 1
River Rch & RM=El Camino,North Branch    ,15
     120
Boundary for River Rch & Prof#=El Camino,North Branch    , 1
Up Type= 2
Dn Type= 2
DSS Import GetInterval= 0
DSS Import GetPeak= 0
DSS Import FillOption= 0

--- North.f02 (steady flow) ---

Flow Title=Flow 02
Program Version=3.11
Number of Profiles= 1
Profile Names=PF 1
River Rch & RM=El Camino,Glendale        ,32
     660
Boundary for River Rch & Prof#=El Camino,Glendale        , 1
Up Type= 3
Up Slope=0.03
Dn Type= 3
Dn Slope=0.03
DSS Import GetInterval= 0
DSS Import GetPeak= 0
DSS Import FillOption= 0

--- North.f03 (steady flow) ---

Flow Title=Flow 03
Program Version=3.11
Number of Profiles= 1
Profile Names=PF 1
River Rch & RM=El Camino,Glendale        ,32
    3700
Boundary for River Rch & Prof#=El Camino,Glendale        , 1
Up Type= 3
Up Slope=0.03
Dn Type= 3
Dn Slope=0.03
DSS Import GetInterval= 0
DSS Import GetPeak= 0
DSS Import FillOption= 0

--- North.f04 (steady flow) ---

Flow Title=Flow 04
Program Version=3.11
Number of Profiles= 1
Profile Names=PF 1
River Rch & RM=El Camino,Glendale        ,32
    3700
Boundary for River Rch & Prof#=El Camino,Glendale        , 1
Up Type= 3
Up Slope=0.03
Dn Type= 3
Dn Slope=0.03
DSS Import GetInterval= 0
DSS Import GetPeak= 0
DSS Import FillOption= 0

--- North.f05 (steady flow) ---

Flow Title=Flow 05
Program Version=3.11
Number of Profiles= 1
Profile Names=PF 1
River Rch & RM=El Camino,Glendale        ,32
    3700
Boundary for River Rch & Prof#=El Camino,Glendale        , 1
Up Type= 3
Up Slope=0.03
Dn Type= 3
Dn Slope=0.03
DSS Import GetInterval= 0
DSS Import GetPeak= 0
DSS Import FillOption= 0

--- North.g01 (geometry) ---

Geom Title=Glendale
Program Version=3.11

River Reach=El Camino       ,Glendale
Reach XY= 5
        .9301397        .5828343        .7185629        .6506986
        .3193613        .5948104        .0838323        .3572854
        .0838323        .3572854

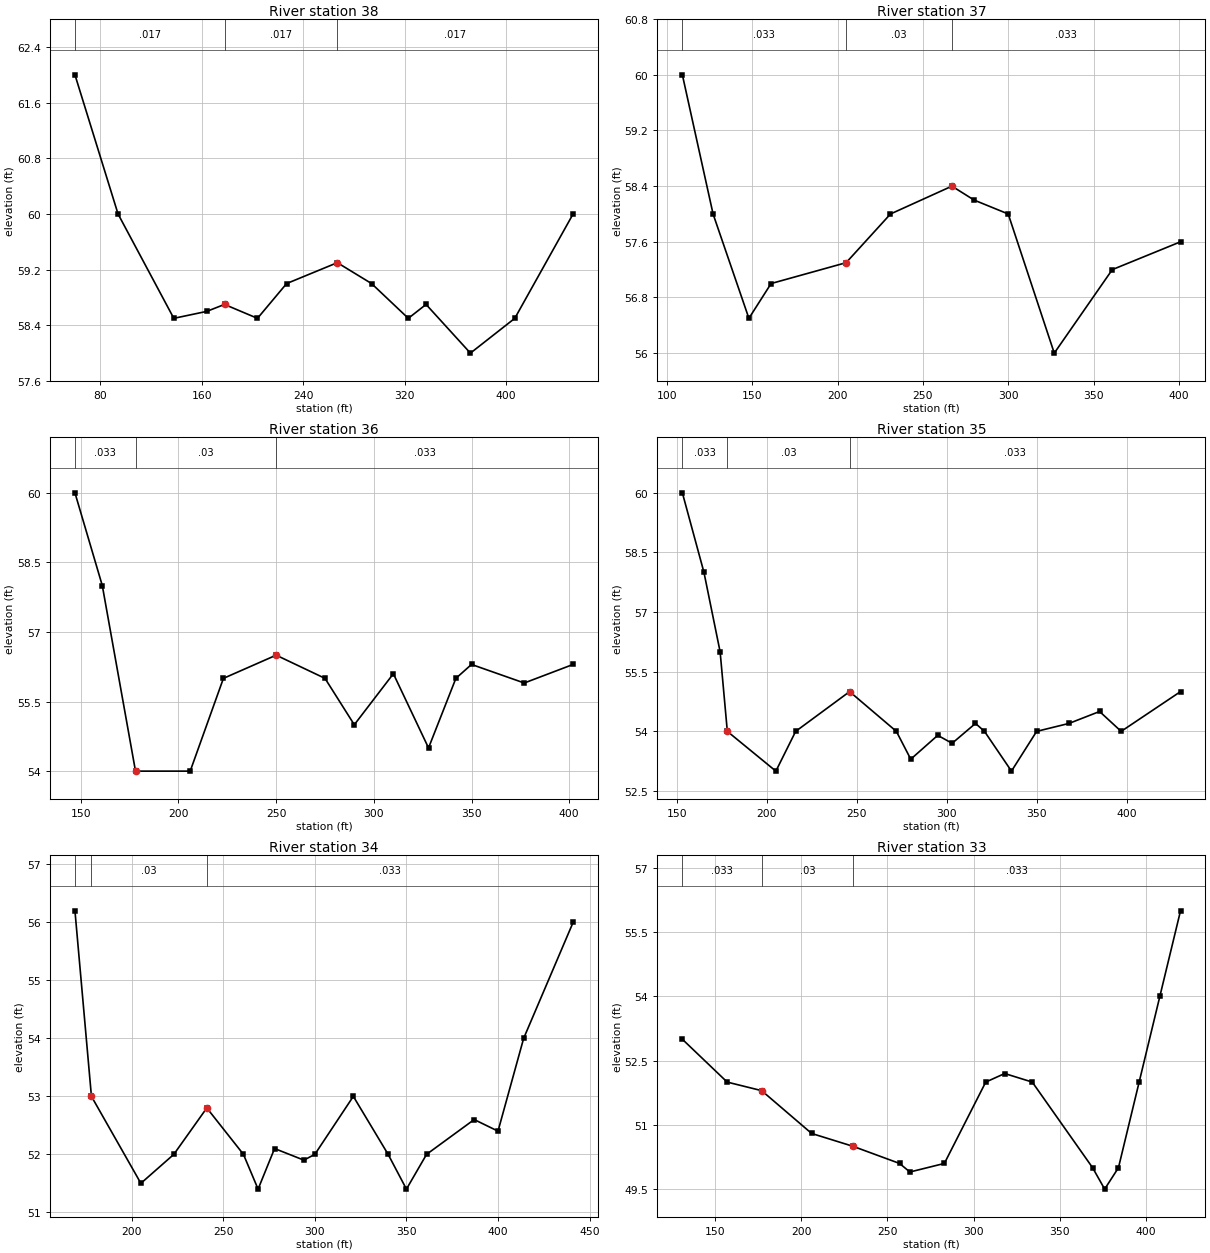
Type RM Length L Ch R = 1 ,38      ,40,40,40
BEGIN DESCRIPTION:
38
END DESCRIPTION:
#Sta/Elev= 14
      60      62      94      60     138    58.5     164    58.6     178    58.7
     204    58.5     227      59     267    59.3     294      59     323    58.5
     337    58.7     372      58     407    58.5     453      60
#Mann= 3 , 0 , 0
      60    .017       0     178    .017       0     267    .017       0
Bank Sta=178,267
XS Rating Curve= 0
Exp/Cntr=0.3,0.1

Type RM Length L Ch R = 1 ,37      ,50,50,50
BEGIN DESCRIPTION:
37
37
END DESCRIPTION:
#Sta/Elev= 12
     109      60     127      58     148    56.5     161      57     205    57.3
     231      58     267    58.4     280    58.2     300      58     327      56
     361    57.2     401    57.6
#Mann= 3 , 0 , 0
     109    .033       0     205     .03       0     267    .033       0
Bank Sta=205,267
XS Rating Curve= 0
Exp/Cntr=0.3,0.1

Type RM Length L Ch R = 1 ,36      ,40,40,40
BEGIN DESCRIPTION:
36
END DESCRIPTION:
#Sta/Elev= 14
     147      60     161      58     178      54     206      54     223      56
     250    56.5     275      56     290      55     310    56.1     328    54.5
     342      56     350    56.3     377    55.9     402    56.3
#Mann= 3 , 0 , 0
     147    .033       0     178     .03       0     250    .033       0
Bank Sta=178,250
XS Rating Curve= 0
Exp/Cntr=0.3,0.1

Type RM Length L Ch R = 1 ,35      ,40,40,40
BEGIN DESCRIPTION:
35
END DESCRIPTION:
#Sta/Elev= 19
     153      60     165      58     174      56     178      54     205      53
     216      54     246      55     272      54     280    53.3     295    53.9
     303    53.7     316    54.2     321      54     336      53     350      54
     368    54.2     385    54.5     397      54     430      55
#Mann= 3 , 0 , 0
     153    .033       0     178     .03       0     246    .033       0
Bank Sta=178,246
XS Rating Curve= 0
Exp/Cntr=0.3,0.1

Type RM Length L Ch R = 1 ,34      ,40,40,40
BEGIN DESCRIPTION:
34
END DESCRIPTION:
#Sta/Elev= 18
     169    56.2     178      53     205    51.5     223      52     241    52.8
     261      52     269    51.4     278    52.1     294    51.9     300      52
     321      53     340      52     350    51.4     361      52     387    52.6
     400    52.4     414      54     441      56
#Mann= 3 , 0 , 0
     169    .033       0     178     .03       0     241    .033       0
Bank Sta=178,241
XS Rating Curve= 0
Exp/Cntr=0.3,0.1

Type RM Length L Ch R = 1 ,33      ,20,30,40
BEGIN DESCRIPTION:
33
END DESCRIPTION:
#Sta/Elev= 17
     131      53     157      52     177    51.8     206    50.8     230    50.5
     257    50.1     263    49.9     283    50.1     307      52     318    52.2
     334      52     369      50     376    49.5     384      50     396      52
     408      54     420      56
#Mann= 3 , 0 , 0
     131    .033       0     177     .03       0     230    .033       0
Bank Sta=177,230
XS Rating Curve= 0
Exp/Cntr=0.3,0.1

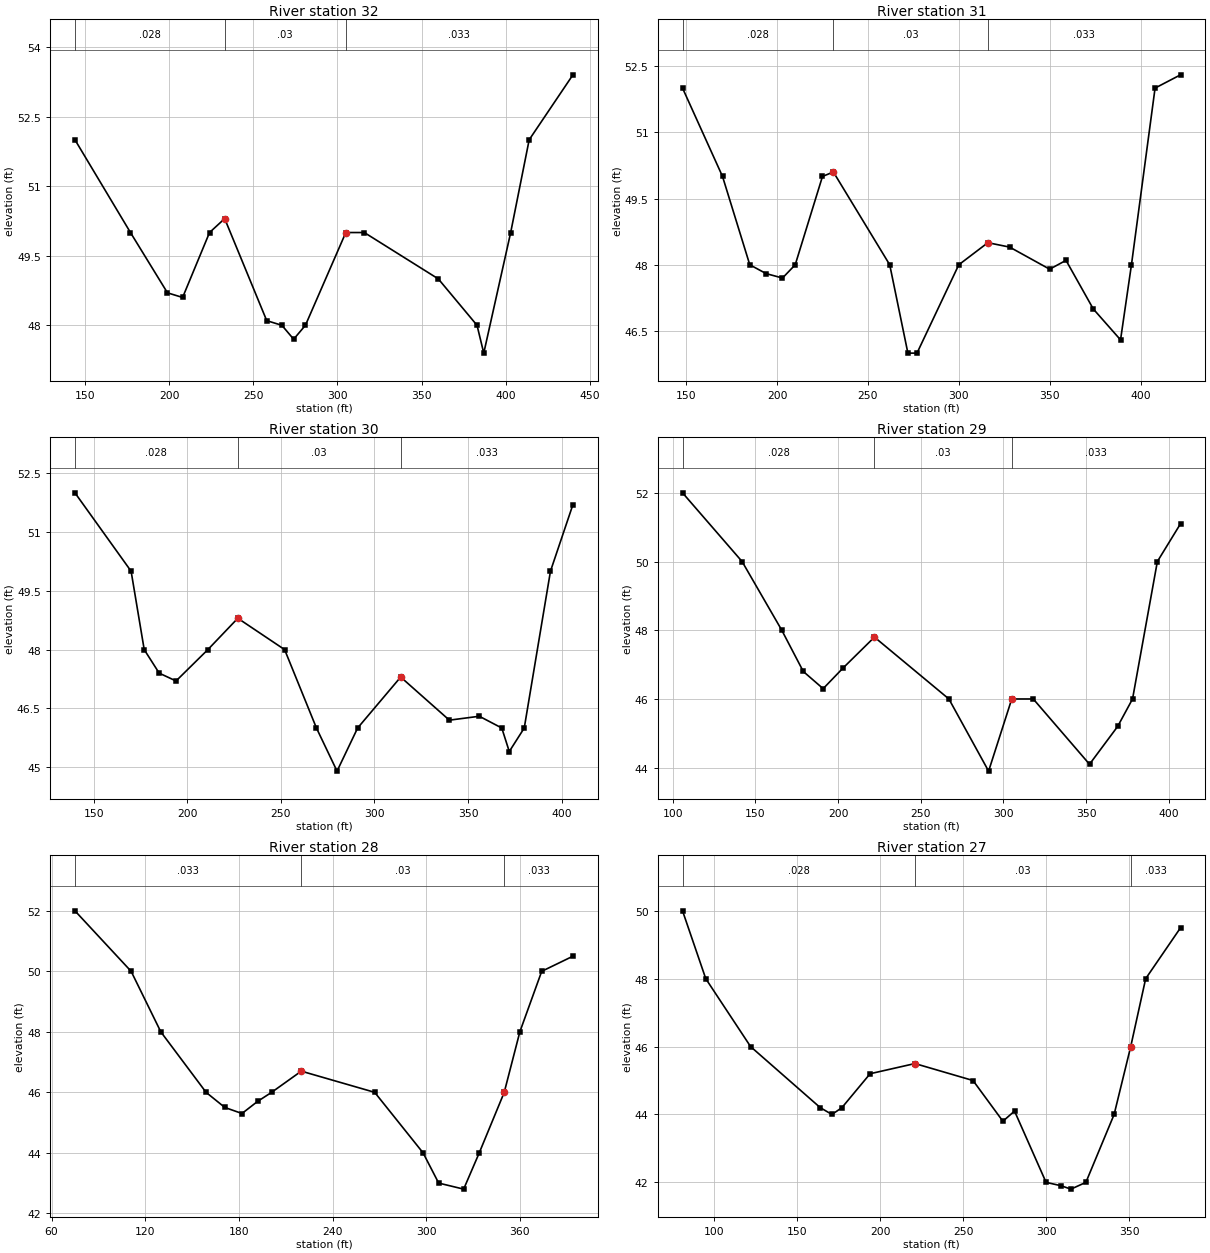
Type RM Length L Ch R = 1 ,32      ,25,25,25
BEGIN DESCRIPTION:
32
END DESCRIPTION:
#Sta/Elev= 18
     144      52     177      50     199    48.7     208    48.6     224      50
     233    50.3     258    48.1     267      48     274    47.7     281      48
     305      50     316      50     360      49     383      48     387    47.4
     403      50     414      52     440    53.4
#Mann= 3 , 0 , 0
     144    .028       0     233     .03       0     305    .033       0
Bank Sta=233,305
XS Rating Curve= 0
Exp/Cntr=0.3,0.1

Type RM Length L Ch R = 1 ,31      ,25,25,25
BEGIN DESCRIPTION:
31
END DESCRIPTION:
#Sta/Elev= 21
     148      52     170      50     185      48     194    47.8     203    47.7
     210      48     225      50     231    50.1     262      48     272      46
     277      46     300      48     316    48.5     328    48.4     350    47.9
     359    48.1     374      47     389    46.3     395      48     408      52
     422    52.3
#Mann= 3 , 0 , 0
     148    .028       0     231     .03       0     316    .033       0
Bank Sta=231,316
XS Rating Curve= 0
Exp/Cntr=0.3,0.1

Type RM Length L Ch R = 1 ,30      ,25,25,25
BEGIN DESCRIPTION:
30
END DESCRIPTION:
#Sta/Elev= 19
     140      52     170      50     177      48     185    47.4     194    47.2
     211      48     227    48.8     252      48     269      46     280    44.9
     291      46     314    47.3     340    46.2     356    46.3     368      46
     372    45.4     380      46     394      50     406    51.7
#Mann= 3 , 0 , 0
     140    .028       0     227     .03       0     314    .033       0
Bank Sta=227,314
XS Rating Curve= 0
Exp/Cntr=0.3,0.1

Type RM Length L Ch R = 1 ,29      ,25,25,25
BEGIN DESCRIPTION:
29
END DESCRIPTION:
#Sta/Elev= 16
     106      52     142      50     166      48     179    46.8     191    46.3
     203    46.9     222    47.8     267      46     291    43.9     305      46
     318      46     352    44.1     369    45.2     378      46     393      50
     407    51.1
#Mann= 3 , 0 , 0
     106    .028       0     222     .03       0     305    .033       0
Bank Sta=222,305
XS Rating Curve= 0
Exp/Cntr=0.3,0.1

Type RM Length L Ch R = 1 ,28      ,20,25,30
BEGIN DESCRIPTION:
28
END DESCRIPTION:
#Sta/Elev= 18
      75      52     111      50     130      48     159      46     171    45.5
     182    45.3     192    45.7     201      46     220    46.7     267      46
     298      44     308      43     324    42.8     334      44     350      46
     360      48     374      50     394    50.5
#Mann= 3 , 0 , 0
      75    .033       0     220     .03       0     350    .033       0
Bank Sta=220,350
XS Rating Curve= 0
Exp/Cntr=0.3,0.1

Type RM Length L Ch R = 1 ,27      ,50,25,10
BEGIN DESCRIPTION:
27
END DESCRIPTION:
#Sta/Elev= 19
      81      50      95      48     122      46     164    44.2     171      44
     177    44.2     194    45.2     221    45.5     256      45     274    43.8
     281    44.1     300      42     309    41.9     315    41.8     324      42
     341      44     351      46     360      48     381    49.5
#Mann= 3 , 0 , 0
      81    .028       0     221     .03       0     351    .033       0
Bank Sta=221,351
XS Rating Curve= 0
Exp/Cntr=0.3,0.1

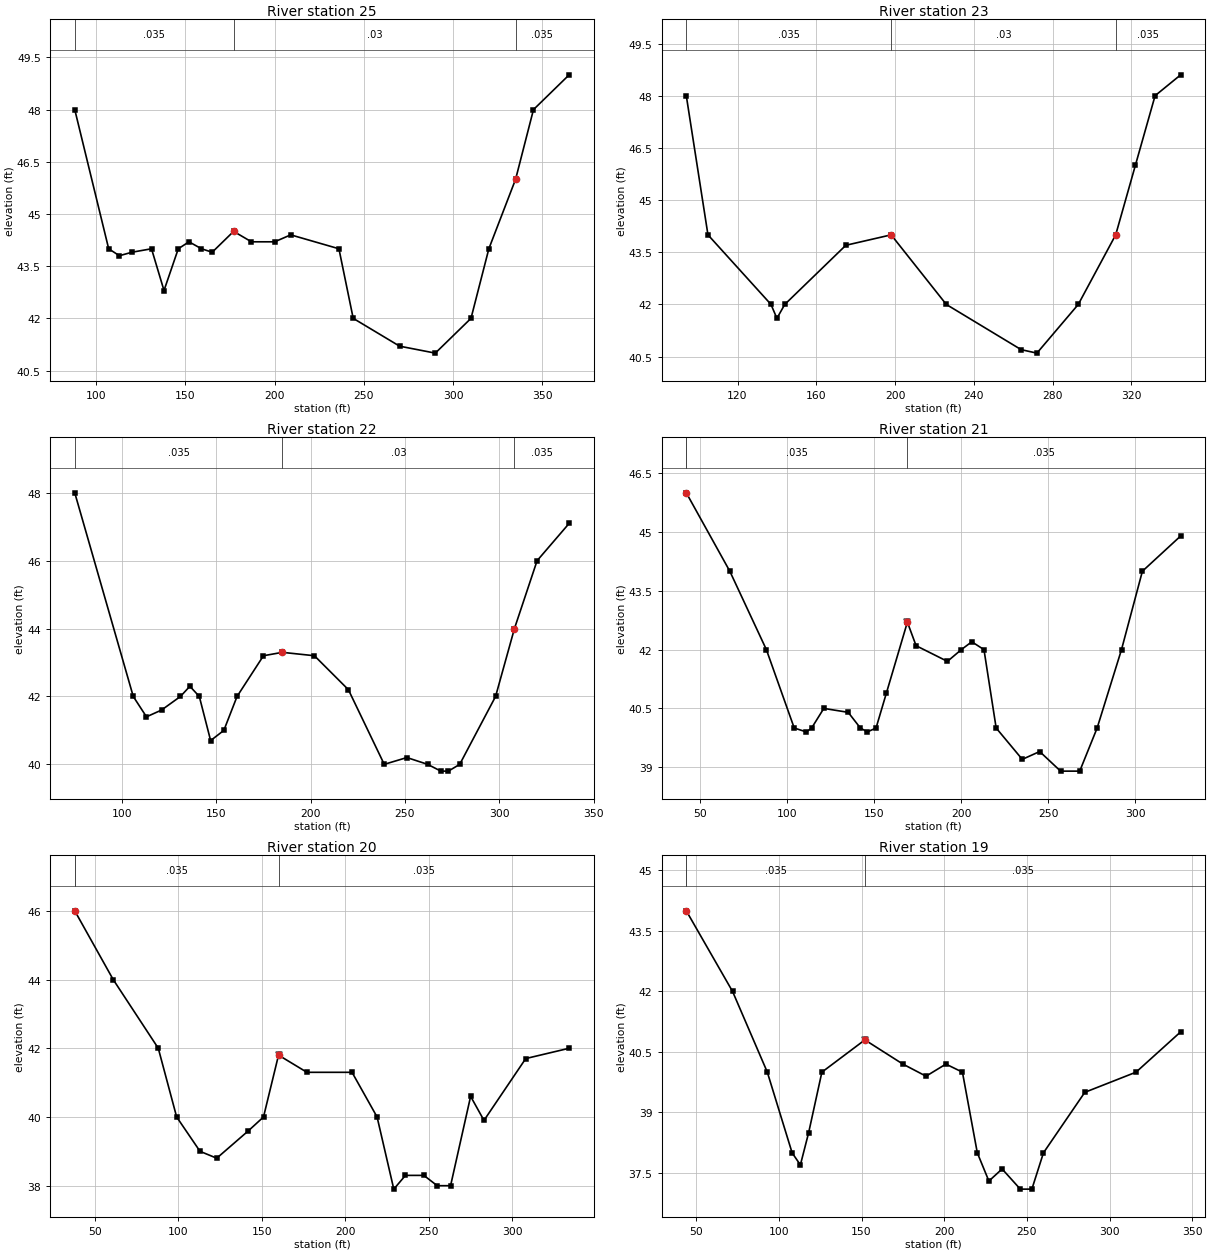
Type RM Length L Ch R = 1 ,25      ,50,25,10
BEGIN DESCRIPTION:
25
END DESCRIPTION:
#Sta/Elev= 23
      88      48     107      44     113    43.8     120    43.9     131      44
     138    42.8     146      44     152    44.2     159      44     165    43.9
     177    44.5     187    44.2     200    44.2     209    44.4     236      44
     244      42     270    41.2     290      41     310      42     320      44
     335      46     345      48     365      49
#Mann= 3 , 0 , 0
      88    .035       0     177     .03       0     335    .035       0
Bank Sta=177,335
XS Rating Curve= 0
Exp/Cntr=0.3,0.1

Type RM Length L Ch R = 1 ,23      ,25,25,25
BEGIN DESCRIPTION:
23
END DESCRIPTION:
#Sta/Elev= 15
      94      48     105      44     137      42     140    41.6     144      42
     175    43.7     198      44     226      42     264    40.7     272    40.6
     293      42     312      44     322      46     332      48     345    48.6
#Mann= 3 , 0 , 0
      94    .035       0     198     .03       0     312    .035       0
Bank Sta=198,312
XS Rating Curve= 0
Exp/Cntr=0.3,0.1

Type RM Length L Ch R = 1 ,22      ,25,25,25
BEGIN DESCRIPTION:
22 - Flow Split From Main Channel, 581-cfs to North Channel
END DESCRIPTION:
#Sta/Elev= 24
      75      48     106      42     113    41.4     121    41.6     131      42
     136    42.3     141      42     147    40.7     154      41     161      42
     175    43.2     185    43.3     202    43.2     220    42.2     239      40
     251    40.2     262      40     269    39.8     273    39.8     279      40
     298      42     308      44     320      46     337    47.1
#Mann= 3 , 0 , 0
      75    .035       0     185     .03       0     308    .035       0
Bank Sta=185,308
XS Rating Curve= 0
Exp/Cntr=0.3,0.1

Type RM Length L Ch R = 1 ,21      ,25,25,25
BEGIN DESCRIPTION:
21 -  Channel Flow 581-cfs from Sec.22
END DESCRIPTION:
#Sta/Elev= 27
      42      46      67      44      88      42     104      40     111    39.9
     114      40     121    40.5     135    40.4     142      40     146    39.9
     151      40     157    40.9     169    42.7     174    42.1     192    41.7
     200      42     206    42.2     213      42     220      40     235    39.2
     245    39.4     257    38.9     268    38.9     278      40     292      42
     304      44     326    44.9
#Mann= 3 , 0 , 0
      42    .035       0      42    .035       0     169    .035       0
Levee=0,,,-1,169,42.7,,
Bank Sta=42,169
XS Rating Curve= 0
Exp/Cntr=0.3,0.1

Type RM Length L Ch R = 1 ,20      ,25,25,25
BEGIN DESCRIPTION:
20 -  Channel Flow 581-cfs from Sec.22
END DESCRIPTION:
#Sta/Elev= 21
      38      46      61      44      88      42      99      40     113      39
     123    38.8     142    39.6     151      40     160    41.8     177    41.3
     204    41.3     219      40     229    37.9     236    38.3     247    38.3
     255      38     263      38     275    40.6     283    39.9     308    41.7
     334      42
#Mann= 3 , 0 , 0
      38    .035       0      38    .035       0     160    .035       0
Levee=0,,,-1,160,41.8,,
Bank Sta=38,160
XS Rating Curve= 0
Exp/Cntr=0.3,0.1

Type RM Length L Ch R = 1 ,19      ,25,25,25
BEGIN DESCRIPTION:
19 -  Channel Capacity of 470-cfs
END DESCRIPTION:
#Sta/Elev= 21
      44      44      72      42      93      40     108      38     113    37.7
     118    38.5     126      40     152    40.8     175    40.2     189    39.9
     201    40.2     211      40     220      38     227    37.3     235    37.6
     246    37.1     253    37.1     260      38     285    39.5     316      40
     343      41
#Mann= 3 , 0 , 0
      44    .035       0      44    .035       0     152    .035       0
Levee=0,,,-1,152,40.8,,
Bank Sta=44,152
XS Rating Curve= 0
Exp/Cntr=0.3,0.1

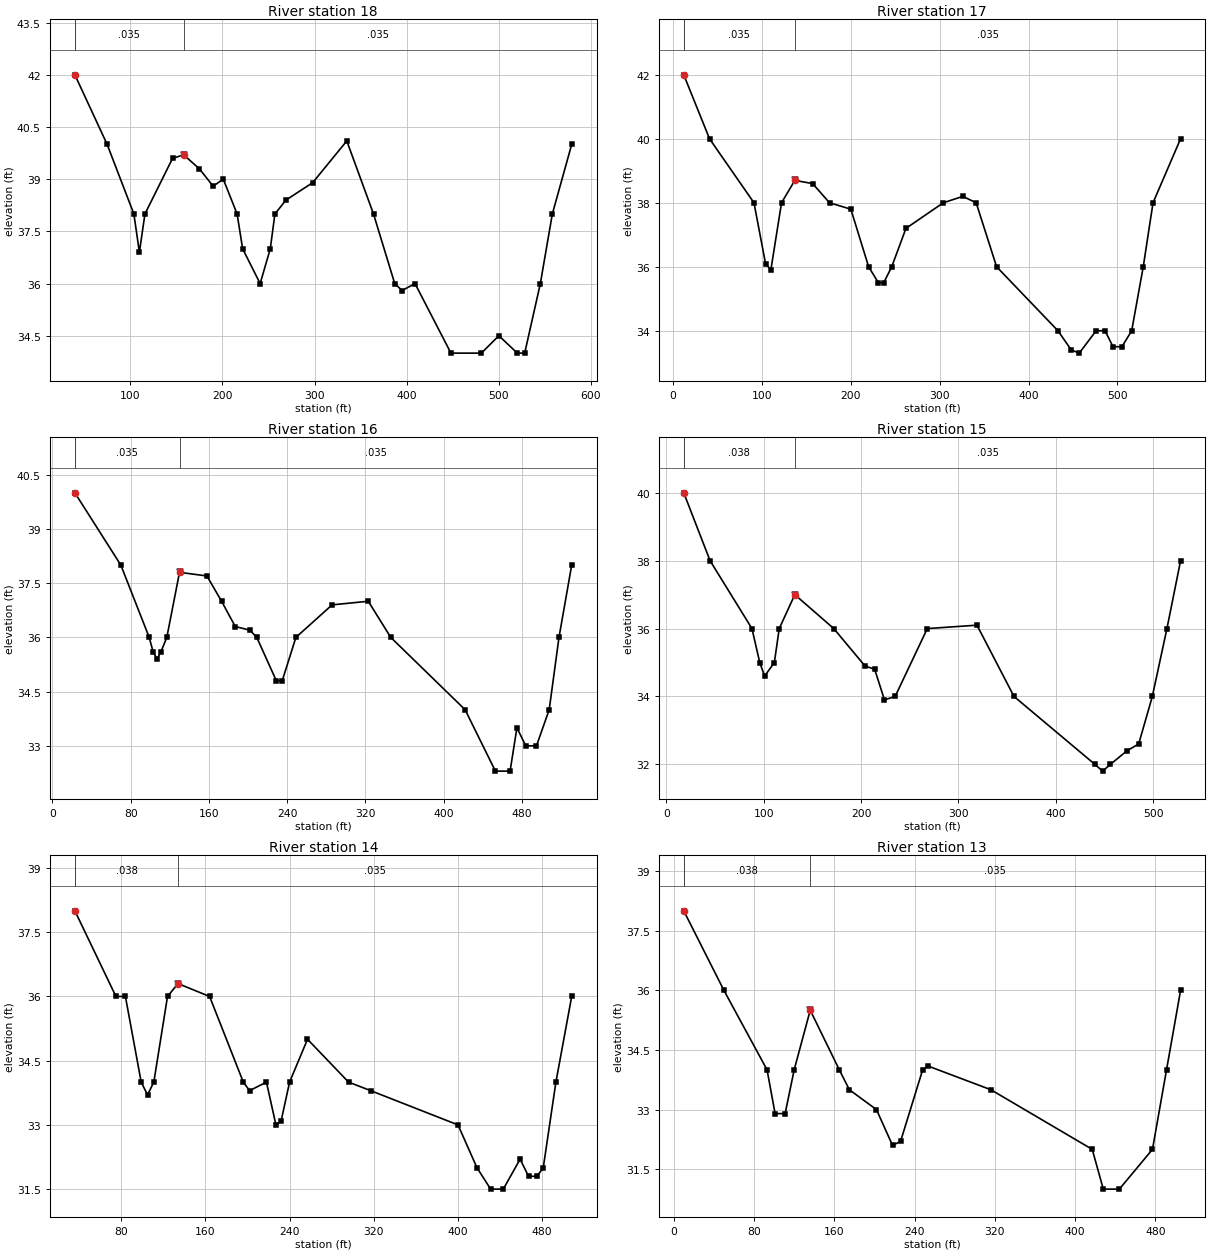
Type RM Length L Ch R = 1 ,18      ,30,25,20
BEGIN DESCRIPTION:
18 -  Channel Capacity of 470-cfs
END DESCRIPTION:
#Sta/Elev= 30
      40      42      75      40     104      38     110    36.9     116      38
     146    39.6     158    39.7     175    39.3     190    38.8     201      39
     216      38     222      37     241      36     252      37     257      38
     269    38.4     298    38.9     335    40.1     364      38     387      36
     395    35.8     409      36     448      34     481      34     500    34.5
     520      34     528      34     545      36     558      38     579      40
#Mann= 3 , 0 , 0
      40    .035       0      40    .035       0     158    .035       0
Levee=0,,,-1,158,39.7,,
Bank Sta=40,158
XS Rating Curve= 0
Exp/Cntr=0.3,0.1

Type RM Length L Ch R = 1 ,17      ,25,25,20
BEGIN DESCRIPTION:
17 -  Channel Capacity of 470-cfs
END DESCRIPTION:
#Sta/Elev= 30
      12      42      41      40      91      38     104    36.1     110    35.9
     122      38     137    38.7     157    38.6     176      38     200    37.8
     220      36     231    35.5     237    35.5     246      36     262    37.2
     304      38     326    38.2     341      38     364      36     433      34
     448    33.4     457    33.3     476      34     486      34     495    33.5
     505    33.5     516      34     529      36     540      38     571      40
#Mann= 3 , 0 , 0
      12    .035       0      12    .035       0     137    .035       0
Levee=0,,,-1,137,38.7,,
Bank Sta=12,137
XS Rating Curve= 0
Exp/Cntr=0.3,0.1

Type RM Length L Ch R = 1 ,16      ,25,25,20
BEGIN DESCRIPTION:
16 -  Channel Capacity of 470-cfs
16
END DESCRIPTION:
#Sta/Elev= 28
      23      40      70      38      99      36     103    35.6     107    35.4
     111    35.6     117      36     130    37.8     158    37.7     173      37
     187    36.3     202    36.2     209      36     229    34.8     235    34.8
     249      36     286    36.9     323      37     346      36     422      34
     453    32.3     468    32.3     475    33.5     484      33     495      33
     508      34     518      36     531      38
#Mann= 3 , 0 , 0
      23    .035       0      23    .035       0     130    .035       0
Levee=0,,,-1,130,37.8,,
Bank Sta=23,130
XS Rating Curve= 0
Exp/Cntr=0.3,0.1

Type RM Length L Ch R = 1 ,15      ,25,25,20
BEGIN DESCRIPTION:
15 -  Channel Capacity of 470-cfs
END DESCRIPTION:
#Sta/Elev= 24
      18      40      45      38      88      36      96      35     101    34.6
     111      35     116      36     132      37     172      36     204    34.9
     214    34.8     224    33.9     235      34     268      36     319    36.1
     357      34     440      32     448    31.8     456      32     473    32.4
     485    32.6     499      34     514      36     528      38
#Mann= 3 , 0 , 0
      18    .035       0      18    .038       0     132    .035       0
Levee=0,,,-1,132,37,,
Bank Sta=18,132
XS Rating Curve= 0
Exp/Cntr=0.3,0.1

Type RM Length L Ch R = 1 ,14      ,25,25,20
BEGIN DESCRIPTION:
14  -  Channel Capacity of 470-cfs
END DESCRIPTION:
#Sta/Elev= 28
      36      38      75      36      84      36      99      34     105    33.7
     111      34     124      36     134    36.3     164      36     196      34
     202    33.8     218      34     227      33     232    33.1     240      34
     257      35     296      34     317    33.8     400      33     418      32
     431    31.5     443    31.5     459    32.2     467    31.8     475    31.8
     481      32     493      34     508      36
#Mann= 3 , 0 , 0
      36    .035       0      36    .038       0     134    .035       0
Levee=0,,,-1,134,36.3,,
Bank Sta=36,134
XS Rating Curve= 0
Exp/Cntr=0.3,0.1

Type RM Length L Ch R = 1 ,13      ,25,25,20
BEGIN DESCRIPTION:
13 -  Channel Capacity of 470-cfs
END DESCRIPTION:
#Sta/Elev= 21
      10      38      50      36      93      34     101    32.9     111    32.9
     120      34     136    35.5     165      34     175    33.5     202      33
     218    32.1     226    32.2     248      34     253    34.1     316    33.5
     417      32     428      31     444      31     477      32     491      34
     505      36
#Mann= 3 , 0 , 0
      10    .035       0      10    .038       0     136    .035       0
Levee=0,,,-1,136,35.5,,
Bank Sta=10,136
XS Rating Curve= 0
Exp/Cntr=0.3,0.1

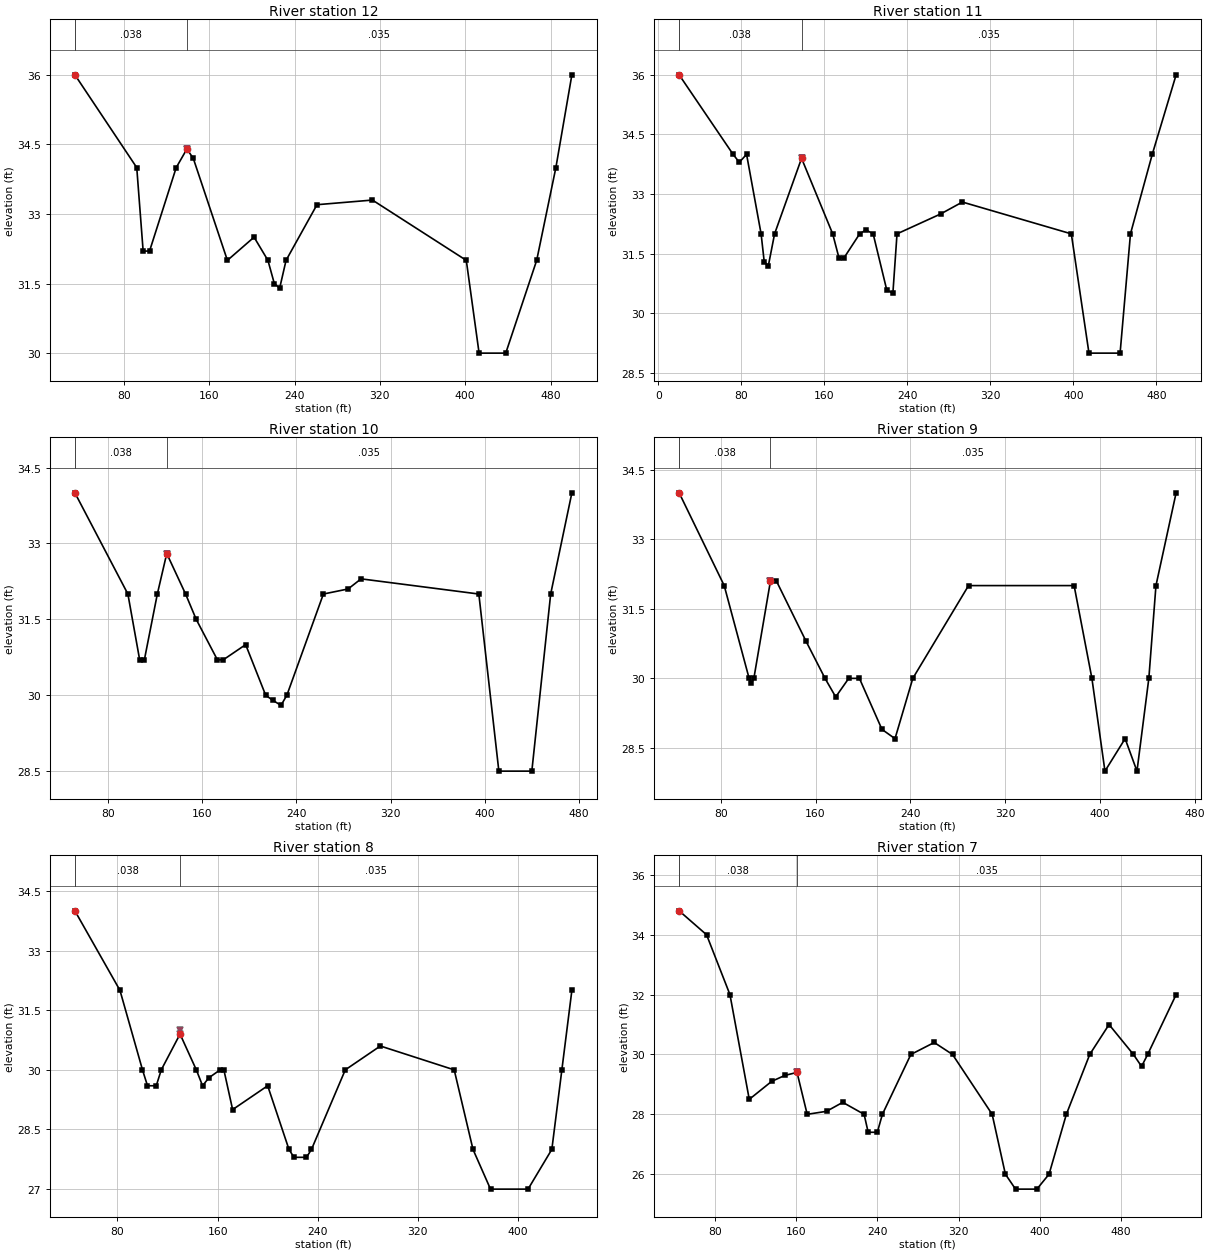
Type RM Length L Ch R = 1 ,12      ,25,25,20
BEGIN DESCRIPTION:
12  -  Channel Capacity of 370-cfs
END DESCRIPTION:
#Sta/Elev= 21
      34      36      92      34      98    32.2     104    32.2     129      34
     139    34.4     145    34.2     177      32     202    32.5     215      32
     221    31.5     226    31.4     232      32     261    33.2     313    33.3
     401      32     413      30     438      30     467      32     485      34
     500      36
#Mann= 3 , 0 , 0
      34    .035       0      34    .038       0     139    .035       0
Levee=0,,,-1,139,34.4,,
Bank Sta=34,139
XS Rating Curve= 0
Exp/Cntr=0.3,0.1

Type RM Length L Ch R = 1 ,11      ,25,25,20
BEGIN DESCRIPTION:
11 -  Channel Capacity of 370-cfs
END DESCRIPTION:
#Sta/Elev= 26
      20      36      72      34      78    33.8      85      34      99      32
     102    31.3     106    31.2     112      32     138    33.9     168      32
     174    31.4     179    31.4     194      32     200    32.1     207      32
     220    30.6     226    30.5     230      32     272    32.5     293    32.8
     398      32     415      29     445      29     455      32     476      34
     499      36
#Mann= 3 , 0 , 0
      20    .035       0      20    .038       0     138    .035       0
Levee=0,,,-1,138,33.9,,
Bank Sta=20,138
XS Rating Curve= 0
Exp/Cntr=0.3,0.1

Type RM Length L Ch R = 1 ,10      ,25,25,20
BEGIN DESCRIPTION:
10 -  Channel Capacity of 370-cfs
END DESCRIPTION:
#Sta/Elev= 23
      52      34      97      32     107    30.7     111    30.7     122      32
     130    32.8     146      32     155    31.5     173    30.7     178    30.7
     197      31     214      30     220    29.9     227    29.8     232      30
     263      32     284    32.1     295    32.3     395      32     412    28.5
     440    28.5     456      32     474      34
#Mann= 3 , 0 , 0
      52    .035       0      52    .038       0     130    .035       0
Levee=0,,,-1,130,32.8,,
Bank Sta=52,130
XS Rating Curve= 0
Exp/Cntr=0.3,0.1

Type RM Length L Ch R = 1 ,9       ,25,25,20
BEGIN DESCRIPTION:
9 -  Channel Capacity of 320-cfs
END DESCRIPTION:
#Sta/Elev= 24
      45      34      83      32     104      30     106    29.9     108      30
     122    32.1     127    32.1     152    30.8     168      30     177    29.6
     188      30     197      30     216    28.9     227    28.7     242      30
     289      32     378      32     393      30     404      28     421    28.7
     431      28     441      30     447      32     464      34
#Mann= 3 , 0 , 0
      45    .035       0      45    .038       0     122    .035       0
Levee=0,,,-1,122,32.1,,
Bank Sta=45,122
XS Rating Curve= 0
Exp/Cntr=0.3,0.1

Type RM Length L Ch R = 1 ,8       ,25,25,20
BEGIN DESCRIPTION:
8 - Padilla East Property Line - Channel Capacity 250-cfs
END DESCRIPTION:
#Sta/Elev= 27
      46      34      82      32     100      30     104    29.6     111    29.6
     115      30     130    30.9     143      30     148    29.6     153    29.8
     162      30     165      30     172      29     200    29.6     217      28
     221    27.8     231    27.8     235      28     262      30     290    30.6
     349      30     364      28     378      27     408      27     427      28
     435      30     443      32
#Mann= 3 , 0 , 0
      46    .035       0      46    .038       0     130    .035       0
Levee=0,,,-1,130,31,,
Bank Sta=46,130
XS Rating Curve= 0
Exp/Cntr=0.3,0.1

Type RM Length L Ch R = 1 ,7       ,30,25,20
BEGIN DESCRIPTION:
7 -  Channel Capacity of 120-cfs
END DESCRIPTION:
#Sta/Elev= 29
      45    34.8      72      34      95      32     114    28.5     136    29.1
     149    29.3     161    29.4     171      28     190    28.1     206    28.4
     227      28     231    27.4     240    27.4     245      28     273      30
     296    30.4     314      30     353      28     366      26     376    25.5
     397    25.5     409      26     426      28     449      30     468      31
     492      30     500    29.6     506      30     534      32
#Mann= 3 , 0 , 0
      45    .035       0      45    .038       0     161    .035       0
Levee=0,,,-1,161,29.4,,
Bank Sta=45,161
XS Rating Curve= 0
Exp/Cntr=0.3,0.1

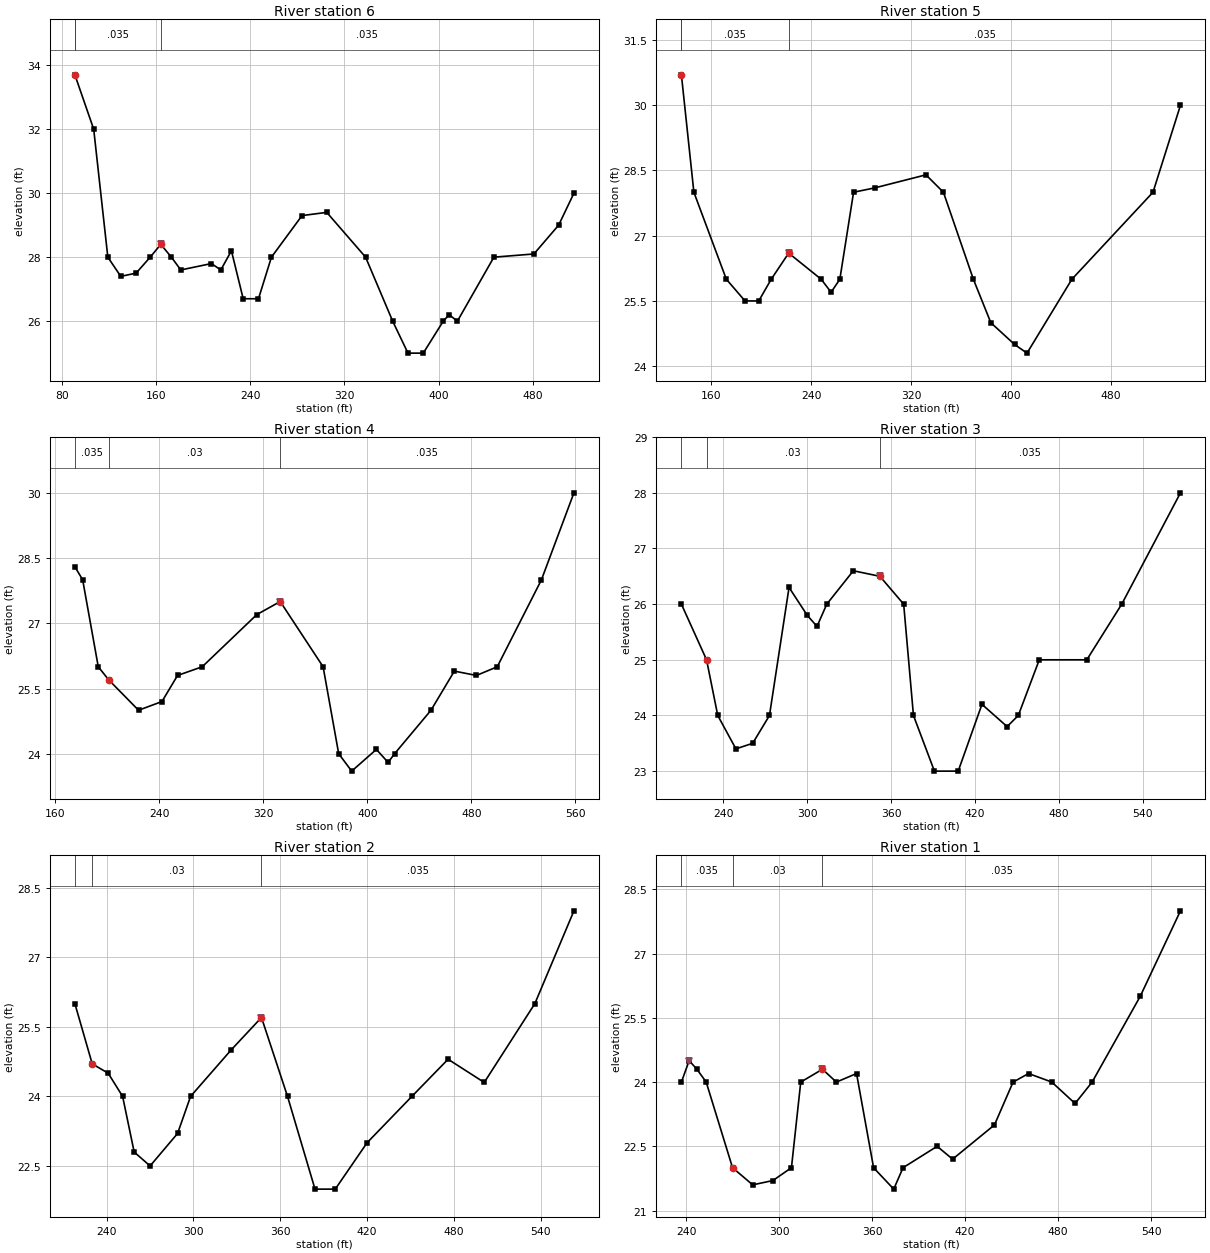
Type RM Length L Ch R = 1 ,6       ,30,25,20
BEGIN DESCRIPTION:
6
END DESCRIPTION:
#Sta/Elev= 28
      91    33.7     107      32     119      28     130    27.4     143    27.5
     155      28     164    28.4     173      28     181    27.6     207    27.8
     215    27.6     224    28.2     234    26.7     247    26.7     258      28
     284    29.3     305    29.4     338      28     361      26     374      25
     387      25     404      26     409    26.2     416      26     447      28
     481    28.1     502      29     515      30
#Mann= 3 , 0 , 0
      91    .035       0      91    .035       0     164    .035       0
Levee=0,,,-1,164,28.4,,
Bank Sta=91,164
XS Rating Curve= 0
Exp/Cntr=0.3,0.1

Type RM Length L Ch R = 1 ,5       ,30,25,20
BEGIN DESCRIPTION:
5
END DESCRIPTION:
#Sta/Elev= 21
     136    30.7     146      28     172      26     187    25.5     198    25.5
     208      26     222    26.6     248      26     256    25.7     263      26
     274      28     291    28.1     332    28.4     346      28     370      26
     384      25     403    24.5     413    24.3     449      26     514      28
     536      30
#Mann= 3 , 0 , 0
     136    .035       0     136    .035       0     222    .035       0
Levee=0,,,-1,222,26.6,,
Bank Sta=136,222
XS Rating Curve= 0
Exp/Cntr=0.3,0.1

Type RM Length L Ch R = 1 ,4       ,30,25,20
BEGIN DESCRIPTION:
4
END DESCRIPTION:
#Sta/Elev= 22
     175    28.3     181      28     193      26     201    25.7     224      25
     242    25.2     254    25.8     273      26     315    27.2     333    27.5
     366      26     378      24     388    23.6     407    24.1     416    23.8
     421      24     449      25     467    25.9     484    25.8     500      26
     534      28     559      30
#Mann= 3 , 0 , 0
     175    .035       0     201     .03       0     333    .035       0
Levee=0,,,-1,333,27.5,,
Bank Sta=201,333
XS Rating Curve= 0
Exp/Cntr=0.3,0.1

Type RM Length L Ch R = 1 ,3       ,30,25,20
BEGIN DESCRIPTION:
3
END DESCRIPTION:
#Sta/Elev= 23
     210      26     228      25     236      24     249    23.4     261    23.5
     273      24     287    26.3     300    25.8     307    25.6     314      26
     333    26.6     352    26.5     369      26     376      24     391      23
     408      23     425    24.2     443    23.8     451      24     466      25
     500      25     525      26     567      28
#Mann= 3 , 0 , 0
     210    .035       0     228     .03       0     352    .035       0
Levee=0,,,-1,352,26.5,,
Bank Sta=228,352
XS Rating Curve= 0
Exp/Cntr=0.3,0.1

Type RM Length L Ch R = 1 ,2       ,25,25,20
BEGIN DESCRIPTION:
2
END DESCRIPTION:
#Sta/Elev= 19
     218      26     230    24.7     241    24.5     251      24     259    22.8
     270    22.5     289    23.2     298      24     326      25     347    25.7
     365      24     384      22     398      22     420      23     451      24
     476    24.8     501    24.3     536      26     563      28
#Mann= 3 , 0 , 0
     218    .035       0     230     .03       0     347    .035       0
Levee=0,,,-1,347,25.7,,
Bank Sta=230,347
XS Rating Curve= 0
Exp/Cntr=0.3,0.1

Type RM Length L Ch R = 1 ,1       ,,,
BEGIN DESCRIPTION:
El Camino Junction South of Glendale
END DESCRIPTION:
#Sta/Elev= 25
     237      24     242    24.5     247    24.3     253      24     270      22
     283    21.6     296    21.7     308      22     314      24     328    24.3
     337      24     350    24.2     361      22     374    21.5     380      22
     402    22.5     412    22.2     439      23     451      24     461    24.2
     476      24     491    23.5     502      24     533      26     559      28
#Mann= 3 , 0 , 0
     237    .035       0     270     .03       0     328    .035       0
Levee=-1,242,24.5,-1,328,24.3,,
Bank Sta=270,328
XS Rating Curve= 0
Exp/Cntr=0.3,0.1

Chan Stop Cuts=-1